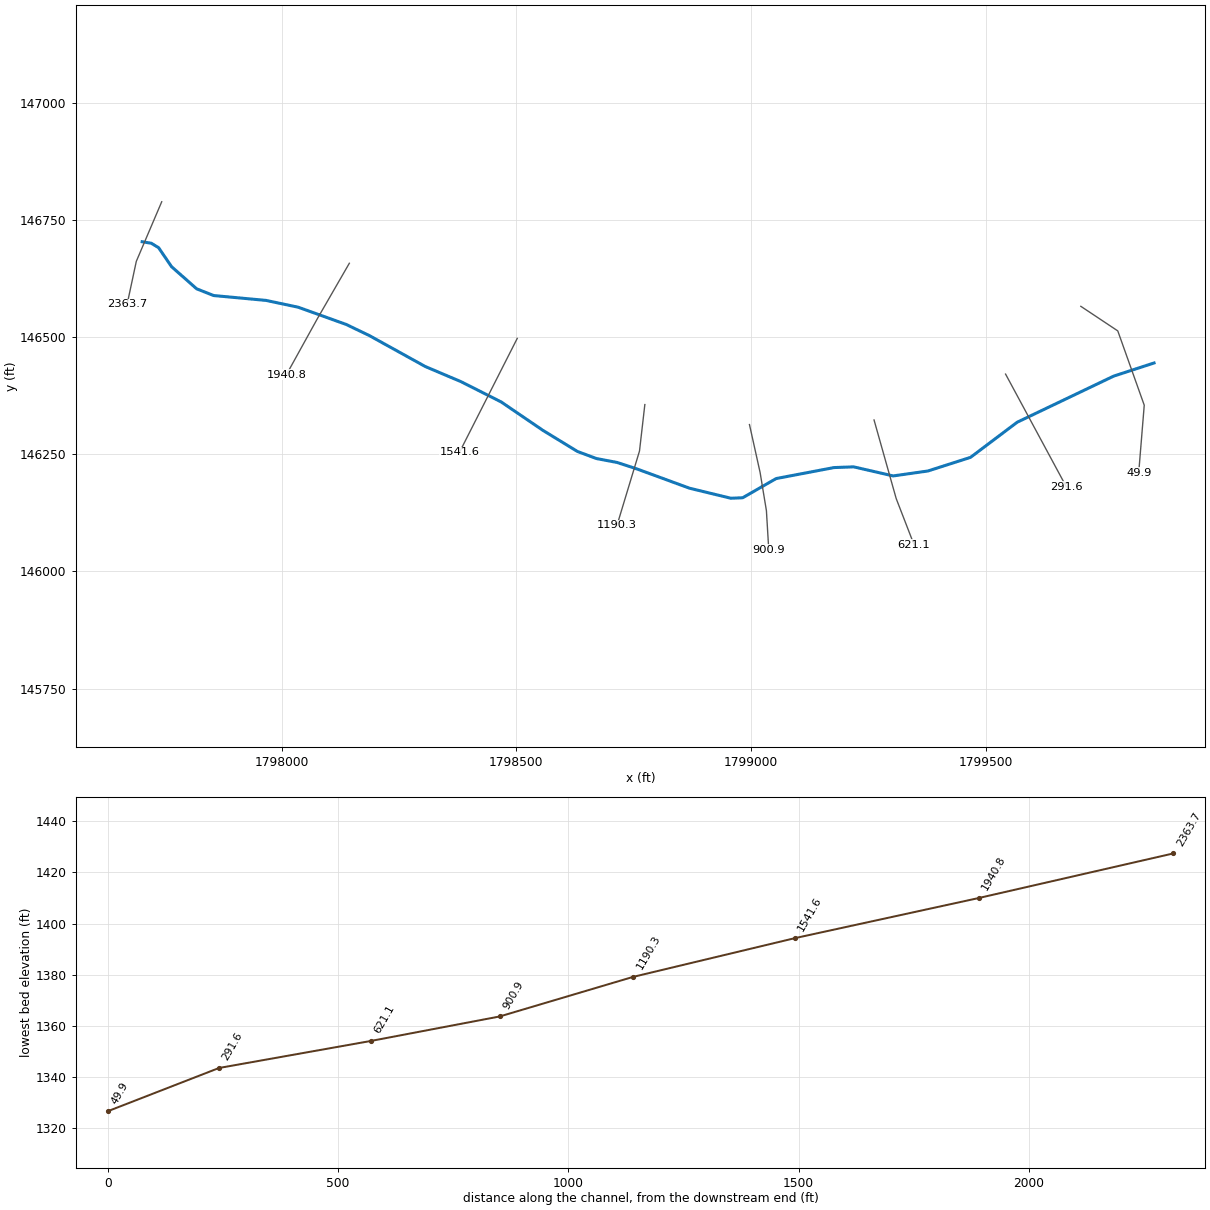
--- Rock Narrows Branch.prj (project) ---

Proj Title=Rock Narrows Branch
Current Plan=p01
Default Exp/Contr=0,0
English Units
Geom File=g01
Flow File=f01
Plan File=p01
BEGIN DESCRIPTION:
END DESCRIPTION:
DSS Export Rating Curves= 0
DSS Export Rating Curve Sorted= 0
DSS Export Volume Flow Curves= 0
DXF OffsetX= 0
DXF OffsetY= 0
DXF ScaleX= 0
DXF ScaleY= 0

--- Rock Narrows Branch.p01 (plan) ---

Plan Title=Floodplain
Program Version=4.00
Geom File=g01
Flow File=f01
K Sum by GR=0
Std Step Tol=0.01
Critical Tol=0.01
Num of Std Step Trials=20
Max Error Tol=0.3
Flow Tol Ratio=0.001
Split Flow NTrial=30
Split Flow Tol=0.02
Split Flow Ratio=0.02
Log Output Level=0
Friction Slope Method=1
Unsteady Friction Slope Method=2
Unsteady Bridges Friction Slope Method=1
Global Log Level=0
CheckData=False
Run HTab=0
Run UNet=0
Run PostProcess=0
UNET Theta=0
UNET Theta Warmup=0
UNET ZTol=0
UNET ZSATol=0
UNET MxIter=0
UNET MaxInSteps=0
UNET DtIC=0
UNET DtMin=0
UNET MaxCRTS=0
UNET WFStab=0
UNET SFStab=0
UNET WFX=0
UNET SFX=0
UNET DSS MLevel=0
UNET DZMax Abort=0
UNET Convert EG Bridges=0
UNET Use Existing IB Tables=0
UNET Froude Limit=0
UNET Froude Power=0
Write IC File=0
Echo Input=False
Echo Output=False
Write Detailed=0

--- Rock Narrows Branch.f01 (steady flow) ---

Flow Title=NFF Regression Equation
Program Version=4.00
Number of Profiles=1
Profile Names=P100yr
River Rch & RM=Rock Narrows ...,Main      ,2363.7
554.7829
River Rch & RM=Rock Narrows ...,Main      ,2363.7
684.6565
River Rch & RM=Rock Narrows ...,Main      ,1190.3
580.8565
River Rch & RM=Rock Narrows ...,Main      ,291.6
691.0296
Boundary for River Rch & Prof#=Rock Narrows ...,Main      ,1
Up Type=0
Dn Type=3
Dn Slope=0.045421

--- Rock Narrows Branch.g01 (geometry) ---

Geom Title=Geometry
Program Version=4.00

River Reach=Rock Narrows ...,Main
Reach XY= 30
     1797703.148      146703.935     1797722.597      146700.693
     1797738.164      146691.195     1797765.633      146650.792
     1797819.224      146603.432     1797855.367      146589.099
     1797966.928      146578.694     1798035.458      146564.173
     1798137.655      146527.407     1798186.884      146503.728
     1798306.379      146437.483     1798382.493      146405.161
     1798467.992      146361.891     1798556.617      146301.416
     1798630.239      146256.274     1798670.934      146241.075
     1798714.778      146232.773     1798757.069      146218.947
     1798869.018      146177.825     1798957.086      146156.401
     1798982.276      146157.379      1799053.69      146198.383
     1799176.897      146221.847     1799218.858      146223.361
     1799302.951      146203.991     1799377.106      146214.585
     1799467.739      146243.634     1799567.167      146318.651
     1799772.878      146417.152     1799858.723      146445.122

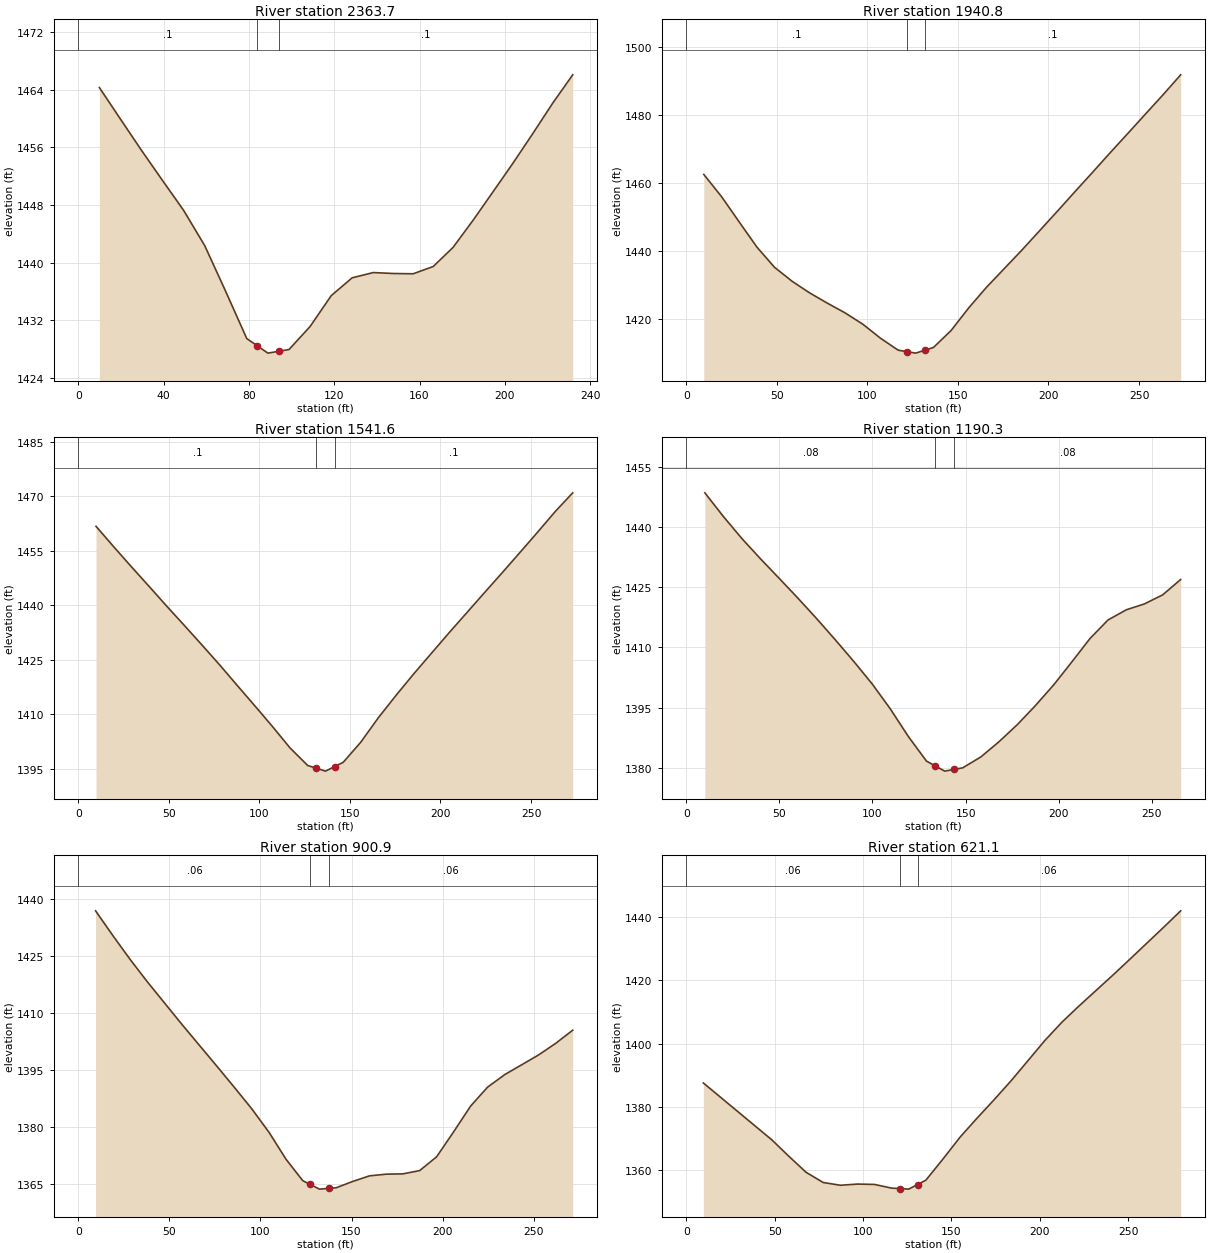
Type RM Length L Ch R = 1 ,2363.7  ,425.5,422.9,420.6
XS GIS Cut Line= 3
     1797744.792      146789.313     1797690.619      146662.042
     1797671.107       146570.59
#Sta/Elev= 26
     9.9 1464.29    19.8 1459.91    29.6  1455.6    39.5  1451.4    49.4 1447.25
    59.3 1442.35    69.2 1435.95      79 1429.46    83.9 1428.46    88.9 1427.44
    93.9 1427.69    98.8 1427.94   108.7 1431.14   118.6 1435.42   128.4 1437.89
   138.3 1438.62   147.7 1438.49     157 1438.45   166.4 1439.46   175.7 1442.11
   185.1 1445.88   194.4 1449.81   203.8  1453.8   213.1 1457.91   222.5 1462.16
   231.8 1466.06
#Mann= 3 , 0 , 0
       0      .1       0    83.9    .045       0    93.9      .1       0
Bank Sta=83.9,93.9
XS Rating Curve= 0 ,0
Exp/Cntr=0.3,0.1

Type RM Length L Ch R = 1 ,1940.8  ,398,399.2,400.1
XS GIS Cut Line= 3
      1798144.45      146657.996     1798076.344      146539.707
     1798010.416      146420.151
#Sta/Elev= 30
     9.7 1462.61    19.5 1456.07    29.2 1448.65      39 1441.23    48.7 1435.29
    58.5 1431.13    68.2 1427.71      78 1424.68    87.7 1421.84    97.5 1418.51
   107.2  1414.4     117 1410.86   121.7 1410.44   126.7 1409.99   131.7 1410.84
   136.5 1411.66   146.2 1416.63     156 1423.34   165.8 1429.39   175.5 1434.83
   185.3 1440.32     195 1445.98   204.8 1451.71   214.5 1457.46   224.3 1463.21
     234 1468.97   243.8 1474.68   253.5 1480.37   263.3  1486.1     273 1491.95
#Mann= 3 , 0 , 0
       0      .1       0   121.7    .045       0   131.7      .1       0
Bank Sta=121.7,131.7
XS Rating Curve= 0 ,0
Exp/Cntr=0.3,0.1

Type RM Length L Ch R = 1 ,1541.6  ,347.8,351.3,354.8
XS GIS Cut Line= 3
     1798502.117      146497.605     1798440.479      146375.815
     1798378.841      146254.024
#Sta/Elev= 30
     9.8 1461.74    19.5 1456.16    29.2 1450.68      39 1445.26    48.7 1439.83
    58.5 1434.48    68.2 1429.11      78 1423.61    87.7 1417.95    97.5 1412.29
   107.3 1406.55     117 1400.65   126.7 1395.85   131.5 1395.09   136.5  1394.3
   141.5 1395.54   146.3 1396.73     156 1402.28   165.7 1409.02   175.5  1415.2
   185.2 1421.08     195 1426.77   204.7 1432.39   214.5 1437.93   224.2 1443.42
     234 1448.92   243.7 1454.44   253.5 1460.06   263.2 1465.73     273 1470.97
#Mann= 3 , 0 , 0
       0      .1       0   131.5    .045       0   141.5      .1       0
Bank Sta=131.5,141.5
XS Rating Curve= 0 ,0
Exp/Cntr=0.3,0.1

Type RM Length L Ch R = 1 ,1190.3  ,280.5,289.4,298.3
XS GIS Cut Line= 3
     1798773.959      146356.358     1798762.565      146257.212
     1798714.626      146098.572
#Sta/Elev= 29
      10 1448.48      20 1442.55    29.9 1437.08    39.9 1432.03    49.9 1427.18
    59.9 1422.27    69.9 1417.21    79.8 1411.99    89.8 1406.57    99.8  1400.9
   109.5 1394.71   119.3 1387.75     129 1381.65   133.8 1380.42   138.8 1379.15
   143.8 1379.58   148.5 1379.98   158.3 1382.72     168  1386.5   177.8 1390.74
   187.5 1395.48   197.3 1400.63     207 1406.32   216.8 1412.19   226.5 1416.81
   236.3 1419.34     246  1420.8   255.8 1423.05   265.5 1426.89
#Mann= 3 , 0 , 0
       0     .08       0   133.8    .045       0   143.8     .08       0
Bank Sta=133.8,143.8
XS Rating Curve= 0 ,0
Exp/Cntr=0.3,0.1

Type RM Length L Ch R = 1 ,900.9   ,276.4,279.8,283.2
XS GIS Cut Line= 4
     1798996.834      146313.647     1799019.491       146211.27
     1799032.917      146129.872     1799037.952      146045.957
#Sta/Elev= 28
     9.5 1436.98    19.1 1430.39    28.6  1424.1    38.1 1418.18    57.2  1406.9
    76.3 1395.94    85.8 1390.42    95.3  1384.8   104.9 1378.52     114 1371.59
   123.2 1365.93   127.4 1364.91   132.4 1363.69   137.4 1363.88   141.5 1364.04
   150.7 1365.72   159.9 1367.19     169 1367.63   178.2 1367.71   187.4 1368.57
   196.7  1372.2     206 1378.75   215.4 1385.58   224.7 1390.56   234.1 1393.85
   252.7 1399.03   262.1 1402.09   271.4 1405.54
#Mann= 3 , 0 , 0
       0     .06       0   127.4    .045       0   137.4     .06       0
Bank Sta=127.4,137.4
XS Rating Curve= 0 ,0
Exp/Cntr=0.3,0.1

Type RM Length L Ch R = 1 ,621.1   ,326,329.5,333.1
XS GIS Cut Line= 3
      1799262.19      146323.481     1799309.392       146155.65
     1799347.363       146057.26
#Sta/Elev= 25
     9.7 1387.56    48.4 1369.66    58.1 1364.45    67.8 1359.42    77.5  1356.2
    87.2 1355.33    96.9  1355.7   106.5 1355.59   116.2 1354.43   120.9 1354.28
   125.9 1354.11   130.9 1355.56   135.6 1356.93   145.3 1363.61     155 1370.53
   164.7 1376.56   174.3 1382.34   183.9 1388.31   203.1 1401.06   212.7 1406.79
   222.3 1411.85   241.5  1421.6     251 1426.55   270.2 1436.67   279.8 1441.83
#Mann= 3 , 0 , 0
       0     .06       0   120.9    .045       0   130.9     .06       0
Bank Sta=120.9,130.9
XS Rating Curve= 0 ,0
Exp/Cntr=0.3,0.1

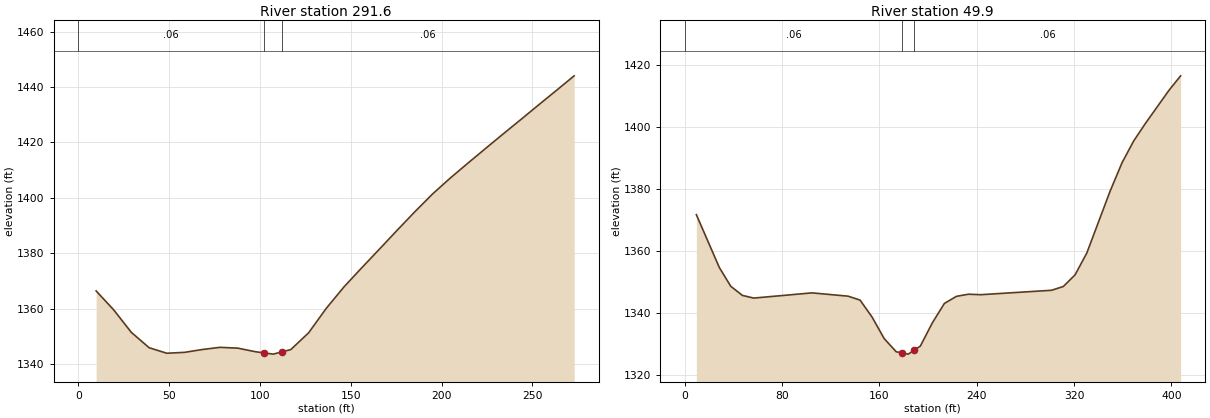
Type RM Length L Ch R = 1 ,291.6   ,244.7,241.6,238.6
XS GIS Cut Line= 3
     1799542.388      146421.387     1799607.063      146301.181
     1799671.739      146180.976
#Sta/Elev= 30
     9.8 1366.38    19.5 1359.52    29.2  1351.4      39 1345.86    48.7 1343.87
    58.5 1344.19    68.2 1345.21      78    1346    87.8 1345.71    97.5 1344.42
   102.2    1344   107.3 1343.55   112.2 1344.38     117  1345.2   126.8 1351.25
   136.5 1360.07   146.3 1367.86     156  1374.7   165.8 1381.48   175.5 1388.26
   185.3 1394.98     195 1401.37   204.8 1407.15   214.5 1412.53   224.3 1417.87
     234 1423.13   243.8 1428.36   253.5  1433.6   263.3 1438.84     273 1444.07
#Mann= 3 , 0 , 0
       0     .06       0   102.2    .045       0   112.2     .06       0
Bank Sta=102.2,112.2
XS Rating Curve= 0 ,0
Exp/Cntr=0.3,0.1

Type RM Length L Ch R = 1 ,49.9    ,50.6,49.9,49.3
XS GIS Cut Line= 4
     1799702.745      146566.048     1799781.416      146513.601
     1799837.796      146354.949     1799825.996      146210.719
#Sta/Elev= 30
     9.5 1371.68    28.4 1354.61    37.8 1348.55    47.3 1345.61    56.7 1344.74
   104.5 1346.42   134.2 1345.36   144.1 1344.09     154 1338.58   163.9 1331.66
   173.8  1327.4   178.7 1327.02   183.7 1326.64   188.7 1327.94   193.6 1329.21
   203.5 1336.74   213.4 1343.01   223.3  1345.3   233.2 1345.99   243.1 1345.83
   301.5 1347.26   311.2 1348.49   320.8 1352.23   330.5 1359.31   349.7 1379.34
   359.4 1388.41     369 1395.47   378.7 1401.17     398 1411.83   407.6 1416.52
#Mann= 3 , 0 , 0
       0     .06       0   178.7    .045       0   188.7     .06       0
Bank Sta=178.7,188.7
XS Rating Curve= 0 ,0
Exp/Cntr=0.3,0.1

Chan Stop Cuts=-1
Use User Specified Reach Order=0